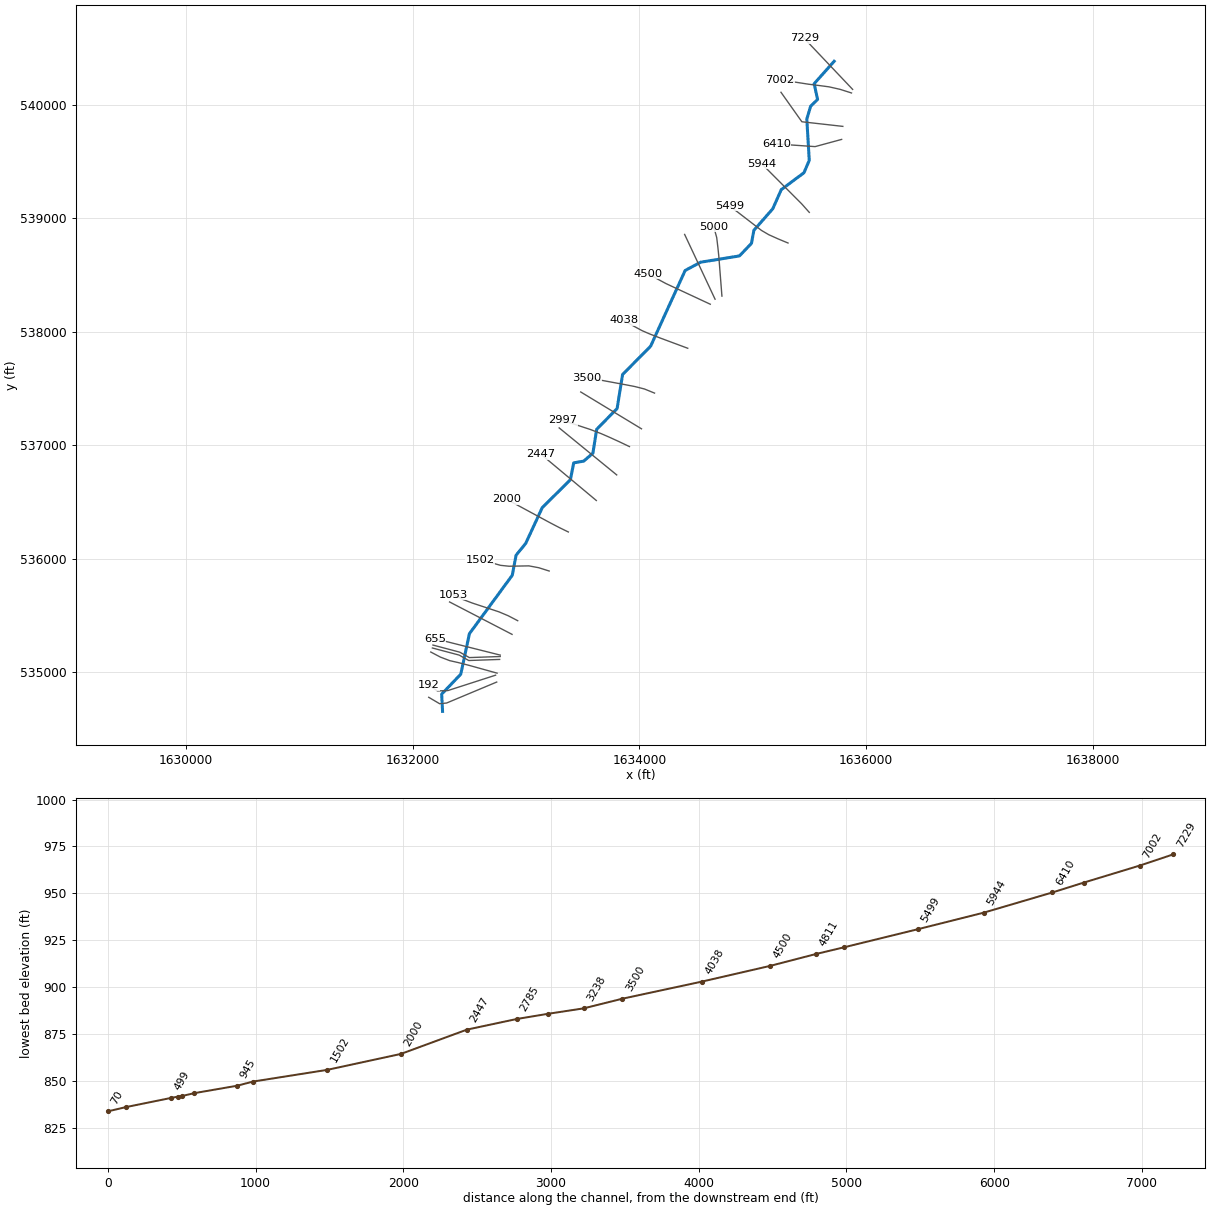
--- LtlGraveCkT1.prj (project) ---

Proj Title=LtlGraveCkT1
Current Plan=p01
Default Exp/Contr=0,0
English Units
Geom File=g01
Flow File=f01
Plan File=p01
Background Map Layer=Inundation Boundary (P100yr Value_0)
BEGIN DESCRIPTION:
---------- MODELED AS PART OF WVEM CTP PROGRAM, 2025----------
Stream Name: Little Grave Creek Tributary 1
Flood Zone: AFH
Marshall County, WV
HEC-RAS Version: RAS 6.6
Vertical Datum: NAVD88
Projection: NAD 1983 StatePlane West Virginia N FIPS 4701 (US Feet)
Terrain: 1-meter West Virginia FEMA R3 South Central (collected 2018-2019)
Land Use: 2024 NLCD
Hydrologic Method:
Duda et al., "Estimation of magnitude and frequency of floods for rural, unregulated streams in and near Virginia and West Virginia." September 8, 2025.
Additional Model Notes:
None
END DESCRIPTION:
DSS Export Rating Curves= 0
DSS Export Rating Curve Sorted= 0
DSS Export Volume Flow Curves= 0
DXF OffsetX= 0
DXF OffsetY= 0
DXF ScaleX= 0
DXF ScaleY= 0

--- LtlGraveCkT1.p01 (plan) ---

Plan Title=Floodplain
Program Version=6.60
Short Identifier=Floodplain
Geom File=g01
Flow File=f01
Subcritical Flow
K Sum by GR= 0
Std Step Tol= 0.01
Critical Tol= 0.01
Num of Std Step Trials= 20
Max Error Tol= 0.3
Flow Tol Ratio= 0.001
Split Flow NTrial= 30
Split Flow Tol= 0.02
Split Flow Ratio= 0.02
Log Output Level= 0
Friction Slope Method= 1
Unsteady Friction Slope Method= 2
Unsteady Bridges Friction Slope Method= 1
Parabolic Critical Depth
Global Vel Dist= 0 , 0 , 0
Global Log Level= 0
CheckData=False
Encroach Param=-1 ,0,0, 0
Flow Ratio Tolerance=0.1
Flow Ratio Min Ratio=0.5
Flow Ratio Max Ratio=4
Flow Ratio Max Iterations= 10
Mapping Interval=1HOUR
Computation Time Step Use Courant=        0
Computation Time Step Use Time Series=    0
Computation Time Step Count To Double=0
Computation Time Step Max Doubling=0
Computation Time Step Max Halving=0
Computation Time Step Residence Courant=0
Run HTab= 0
Run UNet= 0
Run Sediment= 0
Run PostProcess= 0
Run WQNet= 0
Run RASMapper=-1
UNET Theta= 0
UNET Theta Warmup= 0
UNET ZTol= 0
UNET ZSATol= 0
UNET MxIter= 0
UNET Max Iter WO Improvement= 0
UNET MaxInSteps= 0
UNET DtIC= 0
UNET DtMin= 0
UNET MaxCRTS= 0
UNET WFStab= 0
UNET SFStab= 0
UNET WFX= 1
UNET SFX= 1
UNET Gravity=32.17405
UNET 1D Methodology=Finite Difference
UNET DSS MLevel= 1
UNET Pardiso=0
UNET DZMax Abort= 0
UNET Use Existing IB Tables= 0
UNET Froude Reduction=False
UNET Froude Limit= 0
UNET Froude Power= 0
UNET D1 Cores= 0
UNET WindReference=Eulerian
UNET WindDragFormulation=Hsu (1988)
UNET D2 Coriolis=0
UNET D2 Cores= 0
UNET D2 Theta= 1
UNET D2 Theta Warmup= 1
UNET D2 Z Tol= 0.01
UNET D2 Volume Tol= 0.01
UNET D2 Max Iterations= 20
UNET D2 Advanced Convergence=0
UNET D2 WS Max Tol=0.15
UNET D2 WS RMS Tol=0.002
UNET D2 WS Stall Tol=1
UNET D2 Equation= 0
UNET D2 RampUpFraction=0.1
UNET D2 TimeSlices= 1
UNET D2 Turbulence Formulation=Non-Conservative (original)
UNET D2 Eddy Viscosity=0.3
UNET D2 Transverse Eddy Viscosity=0.1
UNET D2 Smagorinsky Mixing=0
UNET D2 BCVolumeCheck=0
UNET D2 Cores=0
UNET D2 SolverType=PARDISO (Direct)
UNET D2 Minimum Iterations= 3
UNET D2 Maximum Iterations= 30
UNET D2 Restart Number= 10
UNET D2 Relaxation Coeff=1.3
UNET D2 SOR Precondition Iterations= 10
UNET D2 ILUT Maximum Fill= 8
UNET D2 ILUT Tolerance=1E-08
UNET D2 Convergence Tolerance=0.00001
PS Theta= 1
PS WS Tol= 0.01
PS Volume Tol= 0.01
PS Max Iterations= 20
PS Equation= 0
PS Advance Time Step=-1
PS Target Courant=0.9
PS Time Slices= 1
PS Iterate With 2D=0
PS Project Initial WSE from DS=-1
PS Ramp Up Initial WSE from US=-1
PS Cores=0
UNET D1D2 MaxIter= 0
UNET D1D2 ZTol=0.01
UNET D1D2 QTol=0.1
UNET D1D2 MinQTol=1
Write IC File= 0
Write IC File at Fixed DateTime=0
Write IC File at Sim End=0
Echo Input=False
Echo Parameters=False
Echo Output=False
Write Detailed= 0
HDF Write Warmup=0
HDF Write Time Slices=0
HDF Flush=0
HDF Compression= 1
HDF Chunk Size= 1
HDF Spatial Parts= 1
HDF Use Max Rows=0
HDF Fixed Rows= 1
Calibration Method= 0
Calibration Iterations= 20
Calibration Max Change=0.05
Calibration Tolerance=0.2
Calibration Maximum=1.5
Calibration Minimum=0.5
Calibration Optimization Method= 1
WQ AD Non Conservative
WQ ULTIMATE=-1
WQ Max Comp Step=1HOUR
WQ Output Interval=15MIN
WQ Output Selected Increments= 0
WQ Create Restart=0
WQ Fixed Restart=0
WQ System Summary=0
WQ Write To DSS=0
Sorting and Armoring Iterations= 10
XS Update Threshold= 0.02
Bed Roughness Predictor= 0
Processes Affected by Predictor=Sediment Only
Hydraulics Update Threshold= 0.02
Energy Slope Method= 1
Volume Change Method= 1
Sediment Retention Method= 0
Sediment TS Multiplier= 1
Warm Up Method= 0
XS Weighting Method= 0
Number of US Weighted Cross Sections= 1
Number of DS Weighted Cross Sections= 1
Upstream XS Weight=0
Main XS Weight=1
Downstream XS Weight=0
Number of DS XS's Weighted with US Boundary= 1
Upstream Boundary Weight= 1
Weight of XSs Associated with US Boundary= 0
Number of US XS's Weighted with DS Boundary= 1
Downstream Boundary Weight= 0.5
Weight of XSs Associated with DS Boundary= 0.5
Percentile Method= 0
Sediment Output Level= 3
Mass or Volume Output= 0
Output Increment Type= 1
Profile and TS Output Increment= 1
Transport Output Increment 1
XS Output Flag= 0
XS Output Increment= 10
Read HDF5 Sediment Hotstart= 0
Sediment Hotstart Type= 0
Write Gradation File= 0
Read Gradation Hotstart= 0
Write HDF5 File= 1
Write Binary Output= 1
Write DSS Sediment File= 0
DSS Sediment Output Type= 1
SV Curve= 0
Specific Gage Flag= 0
Subcell Erosion Methods= 0
Subcell Deposition Methods= 0
Advection Scheme= 1
Matrix Solver= 0
Implicit Weighting Factor= 1
Maximum Outer Loop Convergence Iterations= 5
Convergence Maximum Absolute= 0.001
Convergence RMSE= 0.0001
Grain Fractions Max Abs Error= 0.001
Max Subgrid Regions= 1
Max Subgrid Length Scale= 3.402823E+38
Initial Layer Thickness= 3
Min Layer Thickness= 0.1
Max Layer Thickness= 6
Number of Layers= 5

--- LtlGraveCkT1.f01 (steady flow) ---

Flow Title=Flow
Program Version=6.60
Number of Profiles= 1
Profile Names=P100yr
River Rch & RM=LtlGraveCkT1,Main,7229
     707
River Rch & RM=LtlGraveCkT1,Main,6410
     798
River Rch & RM=LtlGraveCkT1,Main,5944
     905
River Rch & RM=LtlGraveCkT1,Main,4038
    1010
River Rch & RM=LtlGraveCkT1,Main,999
    1130
Boundary for River Rch & Prof#=LtlGraveCkT1,Main            , 1
Up Type= 0
Dn Type= 3
Dn Slope=0.021298
DSS Import GetInterval= 0
DSS Import GetPeak= 0
DSS Import FillOption= 0

--- LtlGraveCkT1.g01 (geometry) ---

Geom Title=Geometry
Program Version=6.60

River Reach=LtlGraveCkT1    ,Main
Reach XY= 30
     1635718.351      540383.065     1635541.975      540185.697
     1635571.963      540046.554     1635510.788      539986.578
     1635477.202      539874.424     1635498.643      539509.773
     1635451.787       539400.13     1635252.181      539252.066
     1635177.211      539083.385     1635010.405       538893.15
     1634988.851      538777.884     1634882.957      538667.305
     1634540.909      538612.015      1634404.09       538538.92
     1634099.564      537871.242     1633852.489       537622.08
     1633804.335      537322.541     1633624.486      537139.205
     1633590.372      536927.827     1633510.005      536858.855
      1633421.34      536843.174     1633392.644      536694.714
     1633144.154      536448.623     1632998.414      536133.751
     1632913.248      536028.794     1632879.662      535852.466
     1632501.816      535337.276     1632425.647      534980.422
     1632257.154      534804.506      1632264.93      534652.821

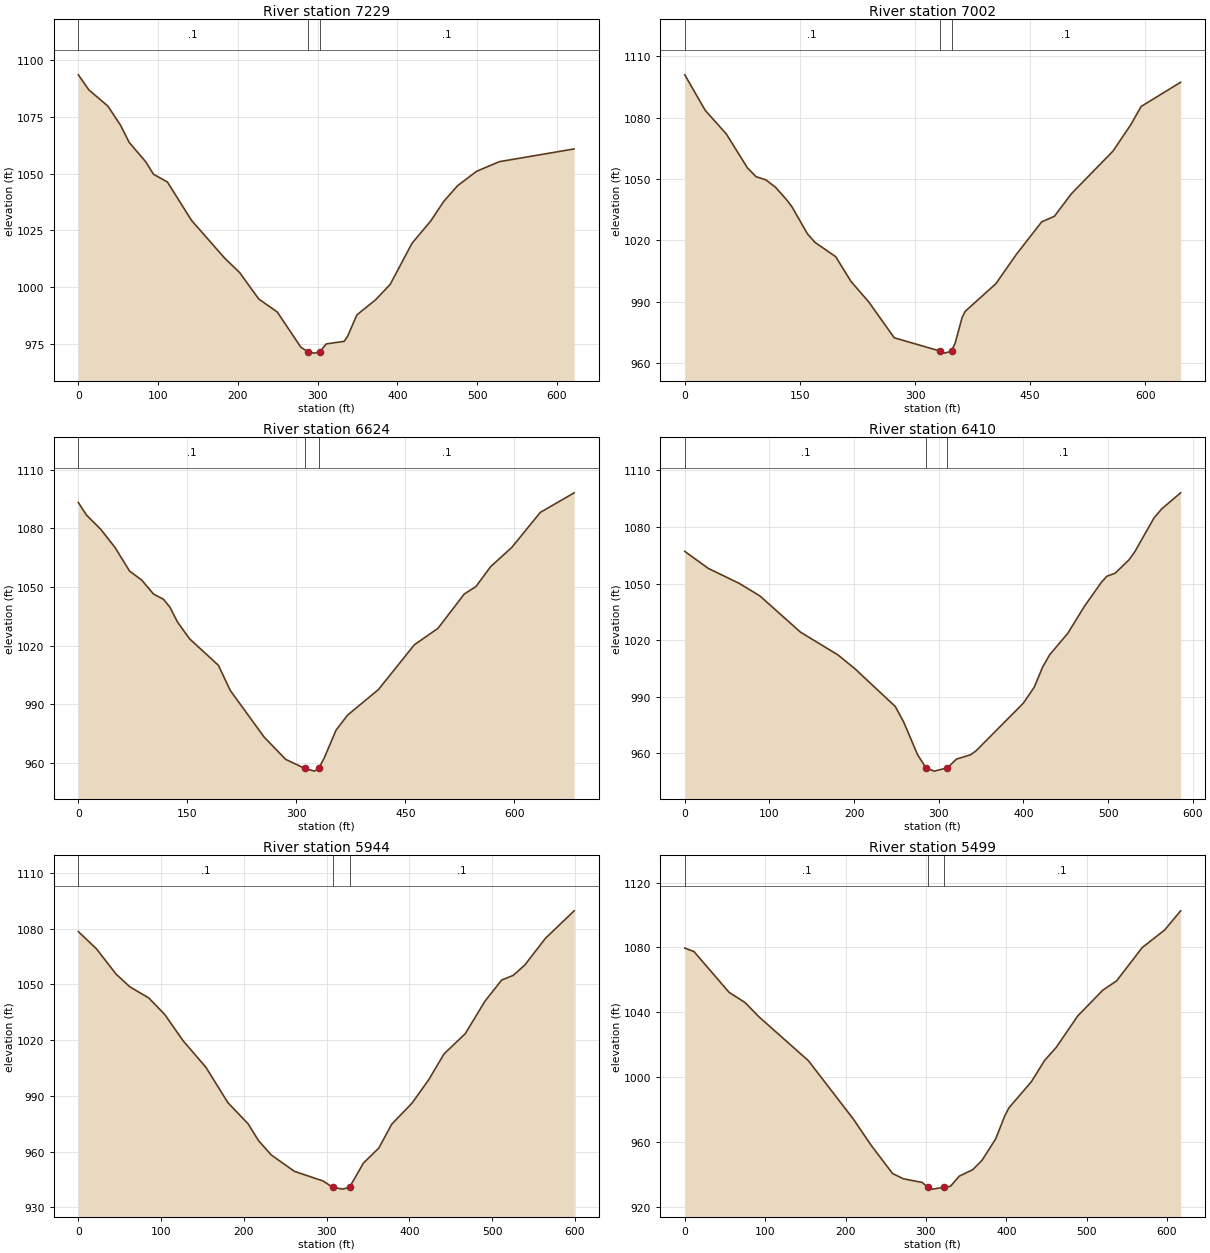
Type RM Length L Ch R = 1 ,7229    ,221.8,227.5,232.6
XS GIS Cut Line= 2
1635881.21315572540135.3769051281635453.29609073540586.238584862
#Sta/Elev= 30
       0 1093.52    13.2 1086.88    37.1 1079.72    52.9 1071.31    63.7 1063.76
    84.5 1055.18    94.2 1049.71   111.7 1046.27   141.9 1029.36     184  1012.5
   202.1 1006.41   226.2   994.7   249.4  988.97     279  973.44  287.68971.4766
   295.8  970.84  303.11971.4871   310.7  974.89   333.3  976.04   337.6  978.29
   349.2  987.69   372.4  994.27   390.9 1001.11   418.3 1019.25   441.9 1029.14
   458.2 1037.76   475.5 1044.66   499.3 1050.99   527.8 1055.24   621.6 1060.85
#Mann= 3 ,-1,0
       0      .1       0  287.68    .045       0  303.11      .1       0
Bank Sta=287.68,303.11
XS Rating Curve= 0 ,0
Exp/Cntr(USF)=0,0
Exp/Cntr=0.3,0.1

Type RM Length L Ch R = 1 ,7002    ,374.2,377.9,375.3
XS GIS Cut Line= 6
 1635871.1625088 540103.740299971635771.06953314540135.607690305
1635674.32661639540157.5833681371635589.85860947540168.895025313
1635490.37160373540181.2923102231635237.27302855540220.935931727
#Sta/Elev= 30
       0 1100.94    26.5 1083.63    54.1 1072.01    81.6 1055.45    92.8 1051.15
   105.7 1049.56   118.3 1045.93   132.6 1039.86   139.4 1036.52   159.8 1023.17
   169.6 1019.01   196.6 1012.01   216.5  999.91   239.7  989.86   272.8  972.36
   331.9  965.93     339  964.85  347.57965.9679   352.2  969.73   361.3  982.36
   365.4  985.33   405.2  998.78   431.7 1013.03   464.9 1029.05   481.5 1031.77
   503.7 1042.83   557.9 1063.69   581.2 1076.67   594.5 1085.47   645.9  1097.3
#Mann= 3 ,-1,0
       0      .1       0   331.9    .045       0  347.57      .1       0
Bank Sta=331.9,347.57
XS Rating Curve= 0 ,0
Exp/Cntr(USF)=0,0
Exp/Cntr=0.3,0.1

Type RM Length L Ch R = 1 ,6624    ,213.3,213.3,213
XS GIS Cut Line= 3
1635794.61978773539809.3166355231635433.58792309539849.940929573
1635249.24168043540110.069700434
#Sta/Elev= 30
       0 1093.28    11.2 1086.84      31  1079.5    50.8 1070.08    70.6 1058.15
    87.1 1053.62   103.6 1046.38   117.1 1043.76     126  1039.7   136.6 1032.02
   153.1 1023.51   192.7 1009.97   209.1  997.05   255.5  973.29   285.2  961.83
   311.6   957.2   324.8  955.81   330.7  957.23     338  962.32   354.5  976.76
   370.4  984.48   412.8  997.53   462.2 1020.44   494.8 1028.91     531 1046.47
     547 1050.26   567.1 1060.41   596.4 1070.34   635.5 1088.21   682.1 1098.23
#Mann= 3 ,-1,0
       0      .1       0   311.6    .045       0   330.7      .1       0
Bank Sta=311.6,330.7
XS Rating Curve= 0 ,0
Exp/Cntr(USF)=0,0
Exp/Cntr=0.3,0.1

Type RM Length L Ch R = 1 ,6410    ,473.8,466,457.1
XS GIS Cut Line= 3
1635784.25589878539694.4289004061635550.00221667539630.919948983
1635207.73593356539654.456885358
#Sta/Elev= 30
       0 1067.04    27.9    1058    64.5 1050.04    88.6 1043.48   136.7 1024.22
   180.9 1012.18   201.3  1004.7   248.7   984.8   258.6  976.57     275  959.28
   284.9  952.24   294.7  950.53  310.17952.2605     321  956.92   337.5  959.18
   344.1  961.28     400  986.58   412.8  995.01     423 1005.92   431.2  1012.3
   452.6 1023.68   472.3 1038.04     492 1050.56   498.6 1053.85   508.5 1055.49
   524.9 1062.62   531.5 1066.73   554.5 1084.89   563.5 1089.59   585.8  1098.1
#Mann= 3 ,-1,0
       0      .1       0   284.9    .045       0  310.17      .1       0
Bank Sta=284.9,310.17
XS Rating Curve= 0 ,0
Exp/Cntr(USF)=0,0
Exp/Cntr=0.3,0.1

Type RM Length L Ch R = 1 ,5944    ,441.8,445.1,443.9
XS GIS Cut Line= 3
1635498.92670472539051.117405221 1635431.8858283539126.413186386
1635079.87056848539479.067854159
#Sta/Elev= 30
       0 1078.44    21.9 1069.16    45.6 1055.53    62.3 1048.67    85.1 1042.71
   104.6 1033.69   126.4 1019.77   154.3 1005.28   180.7  986.32   205.3  974.83
   217.7  965.88   233.1  958.15     261  949.34   295.8  944.11   307.4  940.73
   319.7  939.74327.7724940.8088   344.5  953.79   363.1  961.86   378.6  974.67
   403.2  986.04   423.4  998.67   441.9 1012.59   467.5 1023.44   491.2 1040.88
   511.5 1052.33   525.5 1054.87   539.4 1060.39   564.4 1074.81   599.1 1089.61
#Mann= 3 ,-1,0
       0      .1       0   307.4    .045       0327.7724      .1       0
Bank Sta=307.4,327.7724
XS Rating Curve= 0 ,0
Exp/Cntr(USF)=0,0
Exp/Cntr=0.3,0.1

Type RM Length L Ch R = 1 ,5499    ,507.4,499.4,487
XS GIS Cut Line= 6
1635311.37360214538781.1770002251635223.06209897538817.829485983
1635142.04552872538854.2611716391635077.08962189538892.277827889
1634868.92730856 539052.796535731634793.08100356539108.881397307
#Sta/Elev= 30
       0  1079.6    11.4  1077.5    55.2 1052.28    74.9 1046.07    92.7 1037.04
   153.9 1010.11     210  973.96   231.9  957.95   258.5  940.58     272  937.32
   295.4  935.07   302.4  932.07   308.3  930.94  322.02  932.05   330.5  932.66
   341.5  938.95   358.2  942.92   369.9  948.77   386.9  962.04   398.3  976.36
   403.3  981.08   431.2  997.19   447.5 1010.21   462.1 1018.35   488.8 1037.71
     520 1053.64   537.3 1059.44   569.2    1080     597 1090.76   616.9 1102.61
#Mann= 3 ,-1,0
       0      .1       0   302.4    .045       0  322.02      .1       0
Bank Sta=302.4,322.02
XS Rating Curve= 0 ,0
Exp/Cntr(USF)=0,0
Exp/Cntr=0.3,0.1

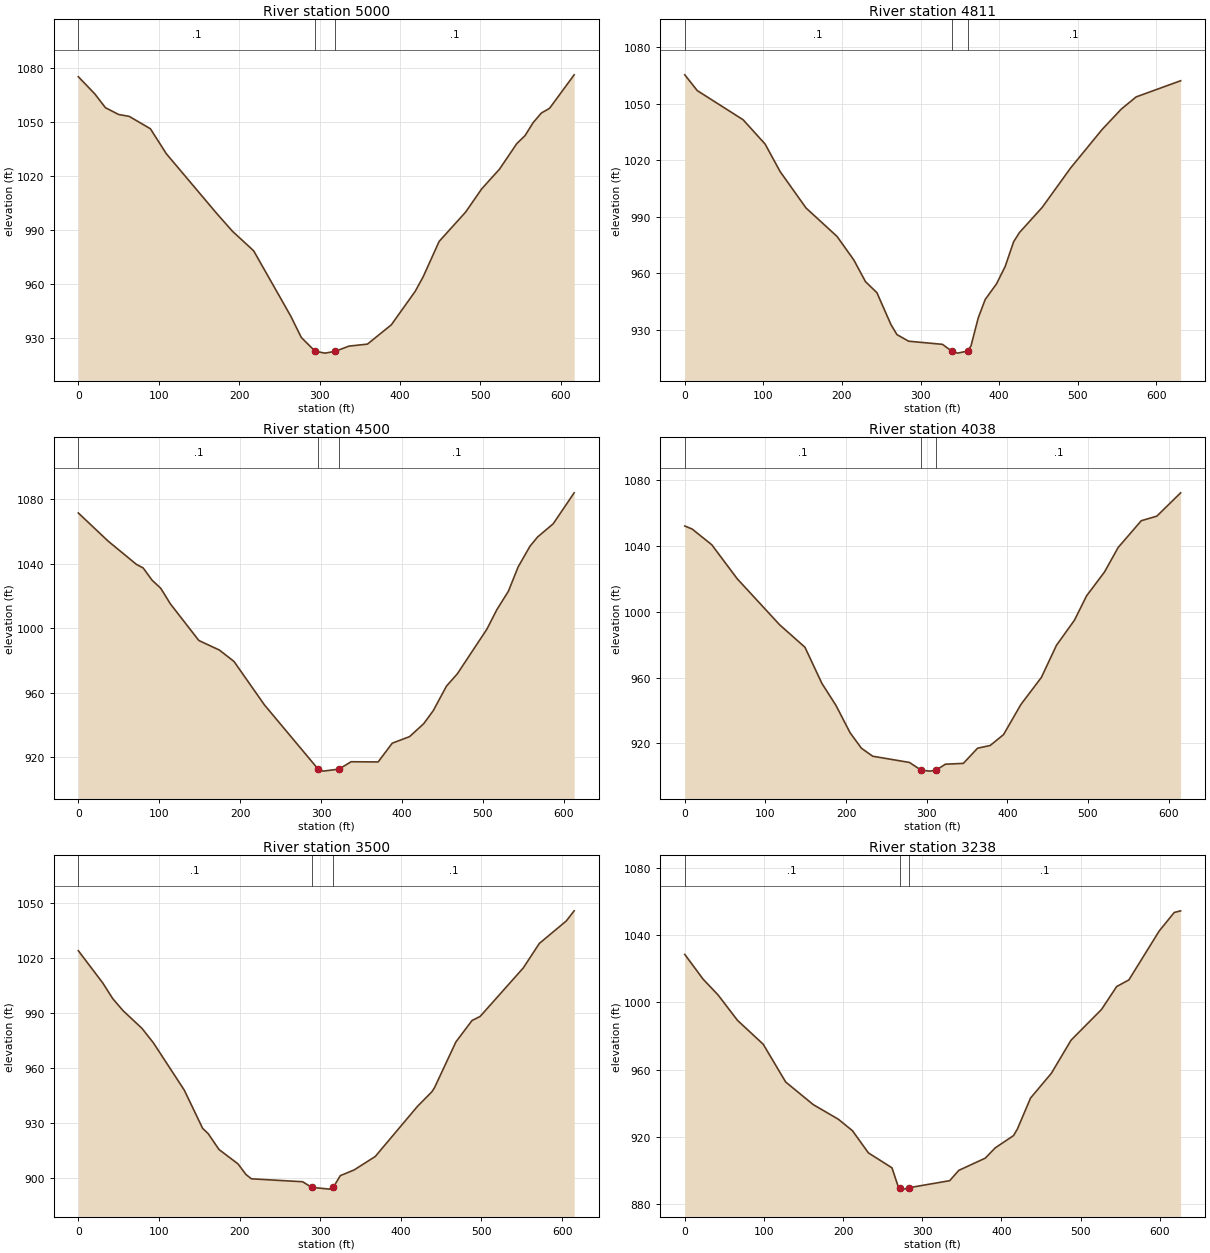
Type RM Length L Ch R = 1 ,5000    ,184.7,189.1,191.9
XS GIS Cut Line= 6
1634728.60705113538312.7287901491634714.43385114538493.423638731
1634700.74982339538667.8878567221634692.94504897538742.505817726
1634682.46180221538829.4524942341634656.44118497538923.591413558
#Sta/Elev= 30
       0 1075.14    20.5 1065.57    33.7  1057.9    50.1 1054.12    63.3 1053.06
    89.6 1046.18   109.4 1032.29   171.9  999.13   191.7  989.11     218  978.26
   264.1  941.93   277.2  930.04  294.52 922.321   306.8  921.31   319.5  922.33
   336.5  925.21   359.5  926.33   389.2  937.08   418.9  955.73   428.8  963.82
   448.6  983.47   481.6  999.82   501.5  1012.7   523.7 1023.71   545.2 1037.92
   555.4 1042.34   565.6 1049.65   575.8 1054.95   585.9 1057.55   616.5 1076.19
#Mann= 3 ,-1,0
       0      .1       0  294.52    .045       0   319.5      .1       0
Bank Sta=294.52,319.5
XS Rating Curve= 0 ,0
Exp/Cntr(USF)=0,0
Exp/Cntr=0.3,0.1

Type RM Length L Ch R = 1 ,4811    ,302.6,310.9,317.5
XS GIS Cut Line= 2
1634668.07640125 538285.752009961634399.75532658538856.816928748
#Sta/Elev= 30
       0  1065.3    15.9 1056.93    74.2 1041.49   102.3 1028.55   121.3 1014.02
   154.3   994.7   193.8   979.6   215.1  967.15     230  955.63   244.5  949.79
   262.3  932.94     270  927.57   284.8  924.07   327.9  922.41   339.5  918.86
   347.2  917.75  359.92  918.85   364.2  921.56   373.5  936.51   382.3  946.18
   396.8  954.55   407.7  963.67   418.5   976.8   425.8  981.64   454.8     995
     491 1015.91   530.9 1036.23   555.5 1047.14   574.4 1053.59     631 1062.16
#Mann= 3 ,-1,0
       0      .1       0   339.5    .045       0  359.92      .1       0
Bank Sta=339.5,359.92
XS Rating Curve= 0 ,0
Exp/Cntr(USF)=0,0
Exp/Cntr=0.3,0.1

Type RM Length L Ch R = 1 ,4500    ,460.8,462,461.9
XS GIS Cut Line= 6
1634625.92418563538241.5366753041634540.94010364538281.119273305
 1634393.6339678538349.7280599771634234.99681789 538423.61472322
1634157.83489873538465.1887870581634075.83571889 538511.17983681
#Sta/Elev= 30
       0 1071.52    36.8 1054.09    71.8 1039.65    80.2  1037.4    91.1 1029.87
   101.9  1024.8   113.8 1015.15     149  992.42   174.3  986.52   192.4  979.46
   229.9  952.59   296.5  912.63   302.6  911.41  322.07 912.644   337.2  917.23
   370.6  917.11     388  928.73   409.5  932.82   426.9  940.82   438.7  948.89
     455  964.09   468.5  971.78     505  999.44   517.3 1011.51   531.6 1022.96
   543.6 1038.01   558.3 1050.92   567.7 1056.63     587 1064.82   612.9 1084.02
#Mann= 3 ,-1,0
       0      .1       0   296.5    .045       0  322.07      .1       0
Bank Sta=296.5,322.07
XS Rating Curve= 0 ,0
Exp/Cntr(USF)=0,0
Exp/Cntr=0.3,0.1

Type RM Length L Ch R = 1 ,4038    ,529.6,538,538.6
XS GIS Cut Line= 6
1634427.16561426537853.3922036671634186.97875868537942.691237666
1634093.67284292537978.6839478251634024.75598601538008.536906489
1633947.00745384538050.505654582 1633864.9495471538098.687316739
#Sta/Elev= 30
       0 1052.14       9 1050.37    33.5 1040.75      65 1020.08   117.5  992.14
     149  978.41     170  956.45   187.5     943     205   926.4     219  916.99
     233  912.11   278.6  908.32   293.2903.5995     304  903.04  311.45903.5966
   323.2  907.25   345.4  907.75   363.1  916.99   378.7  918.63   395.3  925.27
   416.8  943.58   442.2  960.05   460.9  979.57   483.3  994.92   498.2 1009.63
   520.6 1024.28   537.4 1039.08   566.1  1055.4   585.4 1058.17   614.9 1072.36
#Mann= 3 ,-1,0
       0      .1       0   293.2    .045       0  311.45      .1       0
Bank Sta=293.2,311.45
XS Rating Curve= 0 ,0
Exp/Cntr(USF)=0,0
Exp/Cntr=0.3,0.1

Type RM Length L Ch R = 1 ,3500    ,263.9,261.8,259.4
XS GIS Cut Line= 6
1634134.26900098537458.2829924821634045.23702681537494.451227233
1633960.25458522537516.0801209811633886.62448314537530.363556981
1633714.55035222 537562.229634971633536.33023623537595.232521728
#Sta/Elev= 30
       0 1024.11    30.2 1006.57    42.7  997.93    55.3  991.45      79  981.68
    93.1  973.81   131.4  948.01   154.2   927.1     161  924.28   174.5  915.55
     198  907.74     208  901.88   214.7  899.56   278.2  897.96   289.5   894.9
   311.6  893.93  316.29894.9022   324.9  901.28   341.9  904.36   368.3  911.75
   420.7  939.15   438.4  947.02   441.7  949.24   468.4  974.35   488.3  985.99
   498.4  988.22   551.8 1014.65   571.8 1028.07   605.2 1040.33     615 1045.88
#Mann= 3 ,-1,0
       0      .1       0   289.5    .045       0  316.29      .1       0
Bank Sta=289.5,316.29
XS Rating Curve= 0 ,0
Exp/Cntr(USF)=0,0
Exp/Cntr=0.3,0.1

Type RM Length L Ch R = 1 ,3238    ,232.7,240.8,241.4
XS GIS Cut Line= 2
1634019.25766918537143.3991424161633483.50091489537468.065441054
#Sta/Elev= 30
       0 1028.53    23.1 1013.82    42.1 1004.38    66.6  989.27    99.1  975.05
   127.5  952.56   162.4  939.08   194.1  930.38   211.9  923.55     232  910.37
   261.8  901.47   269.5  890.52  271.32 889.659   276.8  888.79  283.54 889.651
   334.7  893.82   346.2  899.95   379.6  907.22   392.2  913.34   415.4  920.68
   420.2  924.54   436.9  943.04   463.2  957.78   488.1   977.5   526.5  995.74
   545.7 1009.41   561.1 1013.35   599.4 1042.46   618.4  1053.5   626.5 1054.49
#Mann= 3 ,-1,0
       0      .1       0  271.32    .045       0  283.54      .1       0
Bank Sta=271.32,283.54
XS Rating Curve= 0 ,0
Exp/Cntr(USF)=0,0
Exp/Cntr=0.3,0.1

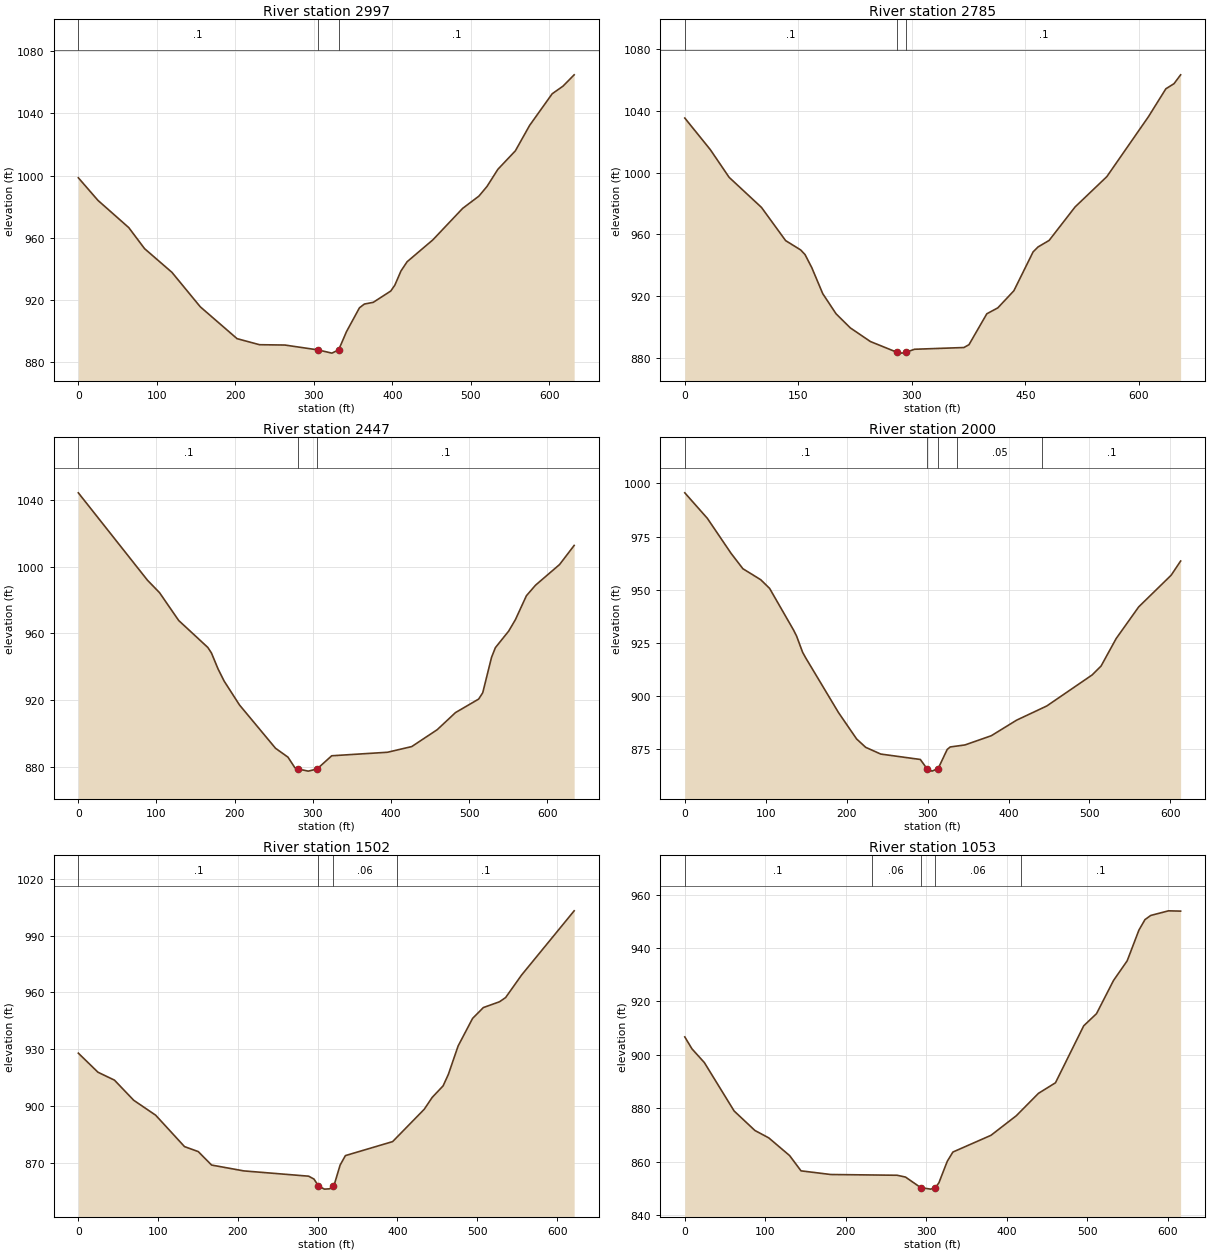
Type RM Length L Ch R = 1 ,2997    ,208.6,212.6,208.2
XS GIS Cut Line= 6
 1633913.0798108536986.7327544841633820.29554756537030.824857891
1633733.02833363537070.6594238881633662.80209614537101.140005976
1633569.32623322537137.0218239721633325.91497464537217.120417058
#Sta/Elev= 30
       0  998.63      25   984.1    64.3  966.56    84.4  953.05   119.3   937.8
   155.4  915.64   202.2  895.19   230.8   891.3   263.1  891.09   305.4  887.95
     323  885.89  331.62887.9799   341.6  899.71   358.1  915.03   364.4  917.45
   375.7  918.55     398  925.82   403.2  929.61     411  938.72   418.8  944.64
   451.6  958.71   489.6  978.97   510.3  986.85   520.6  993.07   534.4 1004.05
   556.7 1015.95   574.8 1032.25   603.6 1052.63   617.4 1057.55   631.6 1064.82
#Mann= 3 ,-1,0
       0      .1       0   305.4    .045       0  331.62      .1       0
Bank Sta=305.4,331.62
XS Rating Curve= 0 ,0
Exp/Cntr(USF)=0,0
Exp/Cntr=0.3,0.1

Type RM Length L Ch R = 1 ,2785    ,335.2,338.1,335.2
XS GIS Cut Line= 2
1633800.67963145536737.0124614281633293.34870543537151.290227652
#Sta/Elev= 30
       0 1035.42    33.8 1014.89    58.6  996.99   101.3  977.52   133.2  956.01
   153.1  949.96   158.9  946.92   167.8  938.46   182.2  921.68   199.8  908.61
   218.6  899.49   245.2  890.63   280.1   883.7   286.4  883.12  292.56883.7012
   303.4  885.62   368.7  886.75   375.4  888.58     399  908.62   413.5  912.44
   434.7  923.51   460.1  948.69   466.7  951.93   481.3  956.14   515.6  977.84
   557.5  997.45   612.6 1036.37   635.5 1054.38   646.2 1057.65     655 1063.42
#Mann= 3 ,-1,0
       0      .1       0   280.1    .045       0  292.56      .1       0
Bank Sta=280.1,292.56
XS Rating Curve= 0 ,0
Exp/Cntr(USF)=0,0
Exp/Cntr=0.3,0.1

Type RM Length L Ch R = 1 ,2447    ,443.3,446.7,446.3
XS GIS Cut Line= 2
1633620.94681595536511.3904164381633134.01110303536918.019977747
#Sta/Elev= 30
       0 1044.21    88.5  991.82   103.9  984.38   128.4  967.72   165.7  951.55
   170.3  948.26   178.8  938.65   186.6  931.37   206.2  917.09   252.3  891.14
   268.2  885.82   277.1  879.48  281.34878.6994   294.2  877.44   305.4   878.7
   324.2  886.64   395.6  888.75   426.6  892.15   459.2  902.28   482.6  912.53
   512.2  920.62   517.4  924.37   528.7  945.62   533.6  951.42   550.7   961.4
   559.3  968.28   573.3  982.54   584.9  988.83   615.7 1001.22   634.4 1012.68
#Mann= 3 ,-1,0
       0      .1       0  281.34    .045       0   305.4      .1       0
Bank Sta=281.34,305.4
XS Rating Curve= 0 ,0
Exp/Cntr(USF)=0,0
Exp/Cntr=0.3,0.1

Type RM Length L Ch R = 1 ,2000    ,492.9,497.9,501.9
XS GIS Cut Line= 6
1633374.24722706536233.8687746381633289.98853731536275.141657978
1633212.39190772536315.5969576391633058.41944663536398.768707305
1632915.44565122 536476.000180141632832.96057998536520.556521475
#Sta/Elev= 30
       0   995.6    27.9  983.57    57.1  967.13    71.8  959.84    93.8  954.67
   104.8  950.57   134.4  930.94   138.1  928.14   145.5  920.54   149.2  917.97
   189.9  892.09   212.3  879.64   223.5  875.71   242.1  872.54     291  869.99
  299.12865.7054   305.4   864.5     313   865.7   324.2  874.71   327.9  875.88
   346.2  876.84   378.7  881.18   409.9   888.5   447.2  895.18   503.2  909.79
   514.3     914     533  926.98   560.8  941.87   600.9  956.79   612.6  963.46
#Mann= 5 ,-1,0
       0      .1       0  299.12    .045       0     313      .1       0
  336.33     .05       0  441.33      .1       0
Bank Sta=299.12,313
XS Rating Curve= 0 ,0
Exp/Cntr(USF)=0,0
Exp/Cntr=0.3,0.1

Type RM Length L Ch R = 1 ,1502    ,505.6,503.2,499.4
XS GIS Cut Line= 6
1633205.30826047535889.731667638 1633113.7920393535918.764089897
1633026.43886755535935.1767867211632851.42937505535932.095428064
1632776.34127064535939.9608978931632597.47450238535990.152398556
#Sta/Elev= 30
       0   927.9    24.6  917.82    45.3  913.63    69.4     903    96.9  895.11
   133.1  878.49   150.3  875.86     167  868.75   207.3  865.66   288.7  862.86
   295.3  861.35  300.92857.7405   308.4  856.02     315  856.19  319.33857.6997
   321.5  859.47   328.1  868.74   334.7  873.74   393.9  881.14   433.5  898.23
   443.5  904.52   457.2  910.63   463.8  916.74     476  931.72   494.1  946.26
   507.6     952   527.9  955.08   535.5  957.29   555.5  969.19   621.4 1003.14
#Mann= 4 ,-1,0
       0      .1       0  300.92    .045       0  319.33     .06       0
  399.97      .1       0
Bank Sta=300.92,319.33
XS Rating Curve= 0 ,0
Exp/Cntr(USF)=0,0
Exp/Cntr=0.3,0.1

Type RM Length L Ch R = 1 ,1053    ,109.1,107.9,106.4
XS GIS Cut Line= 6
1632927.77276745535451.8370222541632843.92188528535495.550517492
 1632763.2032147535529.6140976631632525.70926712535608.049964422
1632443.22518011535639.6981950791632358.00783087535682.227309503
#Sta/Elev= 30
       0  906.74     8.9  902.28    24.3  897.14    61.3  879.02    87.1  871.73
   104.4  868.94   130.2  862.34   144.4  856.62   181.3  855.25   263.8  854.97
   274.2  854.29   293.2850.3304   305.4  849.78   311.4  850.32   315.7  852.16
   326.1  860.21   333.1  863.66   380.4  869.92   411.9  877.26   439.4  885.63
   460.5  889.57   495.6   910.9   511.5  915.44   532.6  927.85   549.6  935.22
   564.2  946.72   571.7  950.64   578.9   952.2   600.9  953.93     616  953.82
#Mann= 5 ,-1,0
       0      .1       0  232.17     .06       0   293.2    .045       0
   311.4     .06       0   417.2      .1       0
Bank Sta=293.2,311.4
XS Rating Curve= 0 ,0
Exp/Cntr(USF)=0,0
Exp/Cntr=0.3,0.1

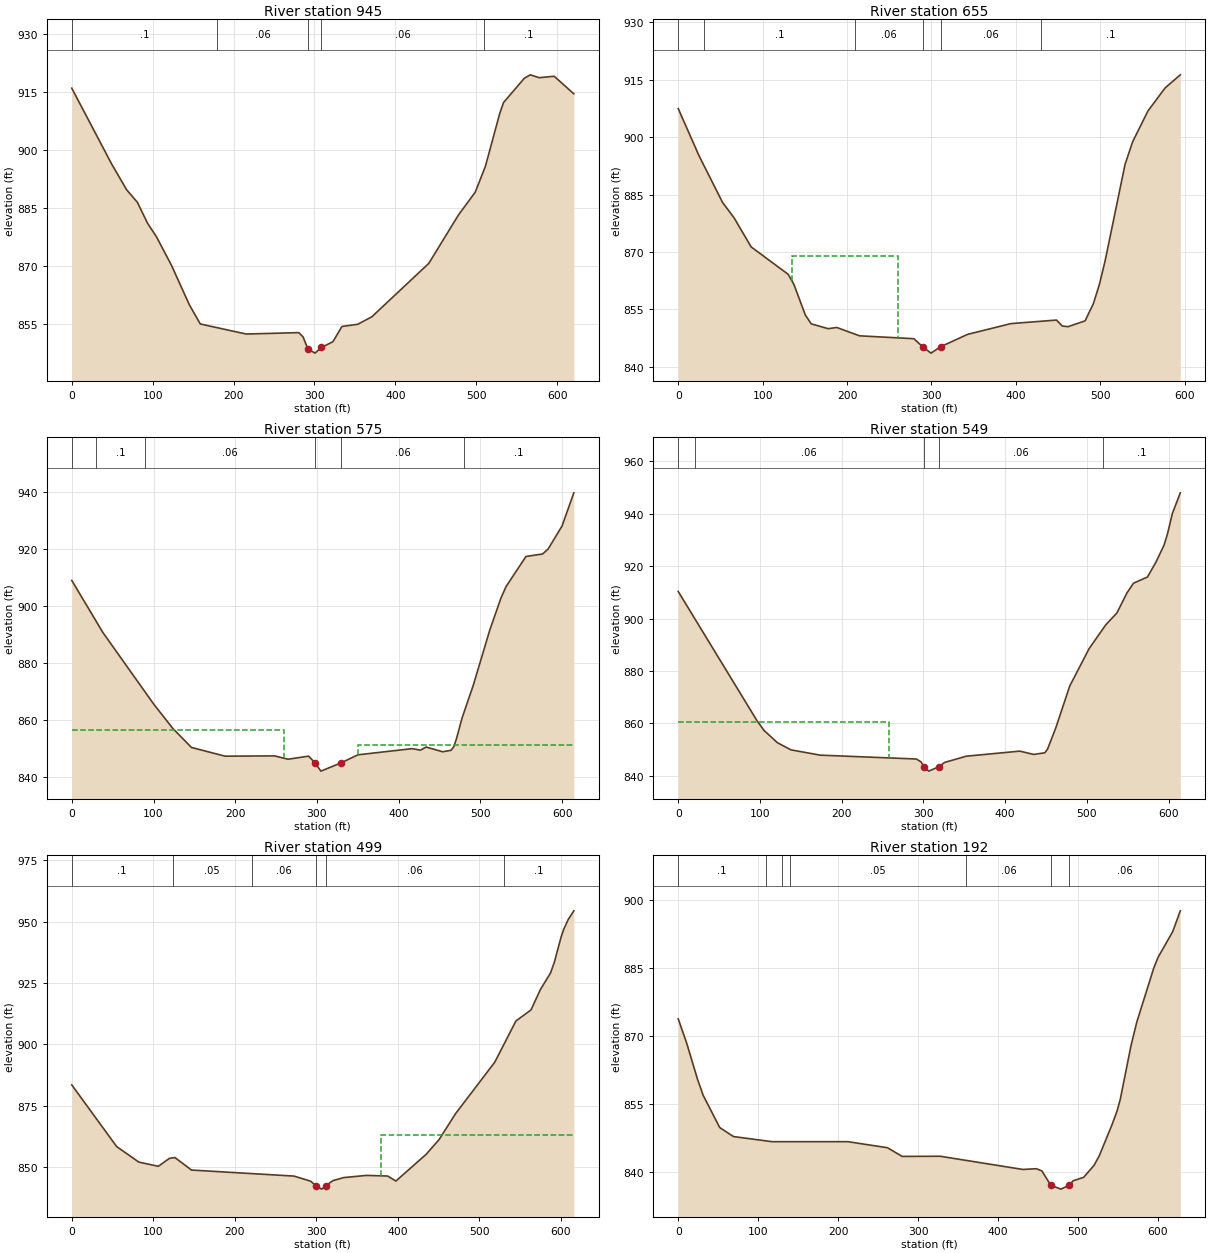
Type RM Length L Ch R = 1 ,945     ,289.2,290.8,289.7
XS GIS Cut Line= 2
1632877.90121945535331.4118759021632326.91322528535617.055651827
#Sta/Elev= 30
       0  915.93    49.3  896.36    67.8  889.72    81.1  886.48    93.7  881.07
   104.8  877.54   123.3  870.19   145.4  860.01   158.9  855.07   215.6  852.48
   280.6  852.84   285.9  851.73   291.7848.7166   300.6  847.55   308.6849.0154
   322.8  850.49   333.9  854.42   353.6     855   370.9  856.93   441.3  870.71
     478  883.21   498.7  889.09   511.3  895.77   528.9  909.33   533.7  912.23
   559.3  918.47   566.7  919.38   577.8  918.64   596.3  919.01   620.6  914.48
#Mann= 5 ,-1,0
       0      .1       0     180     .06       0   291.7    .045       0
   308.6     .06       0     510      .1       0
Bank Sta=291.7,308.6
XS Rating Curve= 0 ,0
Exp/Cntr(USF)=0,0
Exp/Cntr=0.3,0.1

Type RM Length L Ch R = 1 ,655     ,81.5,79.6,72.5
XS GIS Cut Line= 2
1632773.50349424535148.7158567831632196.41606877535293.712697354
#Sta/Elev= 30
       0  907.46    24.8  895.08    52.5  882.97    66.1  878.96    86.4  871.34
   130.3  864.18   137.1  861.53   150.6  853.56   157.6  851.24   177.7  849.98
   187.9  850.29   214.9  848.11   279.2  847.36   289.7  845.26   299.5  843.59
   311.2  845.28   342.9  848.49   394.2   851.3   448.3  852.23   455.1  850.67
   461.9   850.5   482.2  852.02     492  856.54   499.1  861.52     506   867.8
   529.5  892.88   538.5   898.8   556.6  906.83   576.9  912.85     595  916.29
#Mann= 6 ,-1,0
       0     .06       0      30      .1       0     210     .06       0
   289.7    .045       0   311.2     .06       0     430      .1       0
#XS Ineff= 2 ,-1
134.9973260.0977  868.85.24753959.220594  856.49
Permanent Ineff=
       T       T
Bank Sta=289.7,311.2
XS Rating Curve= 0 ,0
Exp/Cntr(USF)=0,0
Exp/Cntr=0.3,0.1

Type RM Length L Ch R = 1 ,575     ,25.6,25.9,31.7
XS GIS Cut Line= 4
1632773.70083384535136.2733405021632501.23137414535126.740881271
1632417.02798426535174.4031774291632180.30524667535237.158534037
#Sta/Elev= 30
       0  909.11    38.1  890.81   100.4  865.61   123.4   857.2   146.4  850.44
   187.6  847.37   248.2  847.47   264.6   846.3   289.8  847.38  297.76844.9909
   304.8  842.12  329.71845.0478   350.1  847.85   416.5  850.02   426.7  849.48
   433.5  850.59   453.8  848.92     464  849.43   467.4  850.69   470.8  853.61
   477.6  860.84   491.2  872.23   511.5  891.72   525.1   902.9   531.3  906.92
   555.7  917.52     576  918.39   582.8  920.12   599.8   928.2   614.3  939.88
#Mann= 6 ,-1,0
       0     .06       0      30      .1       0      90     .06       0
  297.76    .045       0  329.71     .06       0  479.39      .1       0
#XS Ineff= 2 ,-1
       0  259.69  856.49  349.75614.2928  851.17
Permanent Ineff=
       T       T
Bank Sta=297.76,329.71
XS Rating Curve= 0 ,0
Exp/Cntr(USF)=0,0
Exp/Cntr=0.3,0.1

Type RM Length L Ch R = 1 ,549     ,48.4,50.1,53.1
XS GIS Cut Line= 4
1632768.53741842535110.4562634171632496.06795872535100.923804185
1632411.86456884535148.5861003431632175.14183125535211.341456951
#Sta/Elev= 30
       0  910.33    96.3  861.07   105.1  857.29   121.5  852.61   137.9  849.92
   173.6   847.9   291.4  846.42   297.1  845.31  300.59843.4941   306.5   841.8
   318.8  843.48     326  845.13   352.5   847.5   417.9  849.43   434.9  848.16
   448.5   848.8   451.9  850.21   462.1  858.43     479  874.26   502.8  888.58
   523.2  897.65   536.7  902.13   549.1  909.82     557  913.48   574.1  915.85
   584.3  921.43   594.4     928   598.6   932.3   604.6  940.12   614.3  947.97
#Mann= 5 ,-1,0
       0      .1       0      20     .06       0  300.59    .045       0
   318.8     .06       0  519.39      .1       0
#XS Ineff= 2 , 0
          258.14  860.43
Permanent Ineff=
       T       F
Bank Sta=300.59,318.8
XS Rating Curve= 0 ,0
Exp/Cntr(USF)=0,0
Exp/Cntr=0.3,0.1

Type RM Length L Ch R = 1 ,499     ,300.5,307.4,310.6
XS GIS Cut Line= 6
1632746.01226306534989.5900952221632499.11085397535058.176572233
1632402.23867239535083.0498820541632328.97799213535099.498339981
1632246.01457539 535131.116386981632160.84807906535175.858751565
#Sta/Elev= 30
       0  883.52    55.1  858.41    82.3  852.09   106.2  850.36   119.8  853.59
   126.6  853.94     147  848.84   272.8  846.38   293.2  844.31  299.58842.4948
   306.7  841.07   312.2  842.49   320.3  844.51   333.8  845.77   361.8  846.66
   387.8   846.4   397.9  844.36     435  855.25   450.9  861.26   471.2  871.86
   519.3  892.81   545.2  909.57   563.7  914.06   575.4  922.47   587.6  929.04
   592.4  933.54   600.7  943.82     604  946.98   609.4  950.91   616.3  954.43
#Mann= 6 ,-1,0
       0      .1       0  123.75     .05       0  221.25     .06       0
  299.58    .045       0   312.2     .06       0  530.14      .1       0
#XS Ineff= 1 ,-1
379.8158616.2606  862.98
Permanent Ineff=
       T
Bank Sta=299.58,312.2
XS Rating Curve= 0 ,0
Exp/Cntr(USF)=0,0
Exp/Cntr=0.3,0.1

Type RM Length L Ch R = 1 ,192     ,120.9,121.3,120.1
XS GIS Cut Line= 4
1632732.52782544534971.6150871541632311.82609072534835.995648027
 1632219.7911464534832.8815648421632141.66302263534885.024165674
#Sta/Elev= 30
       0  873.79    10.5  868.47    24.3  860.34    31.2  856.89    51.9  849.76
    69.1  847.77   117.3  846.64   212.2  846.64   261.8   845.3     280  843.38
   327.6  843.42     431   840.5     448  840.66   454.8  840.18  466.02837.0164
   478.6  836.15   489.2  837.02   493.9  837.99   507.1  838.76   520.2  841.43
   526.8  843.58   542.8  850.49   548.9  853.42   552.9     856   566.4  867.92
   573.5  873.04   594.8  885.02   600.2   887.4   618.5  893.07     628  897.67
#Mann= 7 ,-1,0
       0      .1       0     110     .05       0     130      .1       0
     140     .05       0     360     .06       0  466.02    .045       0
   489.2     .06       0
Bank Sta=466.02,489.2
XS Rating Curve= 0 ,0
Exp/Cntr(USF)=0,0
Exp/Cntr=0.3,0.1

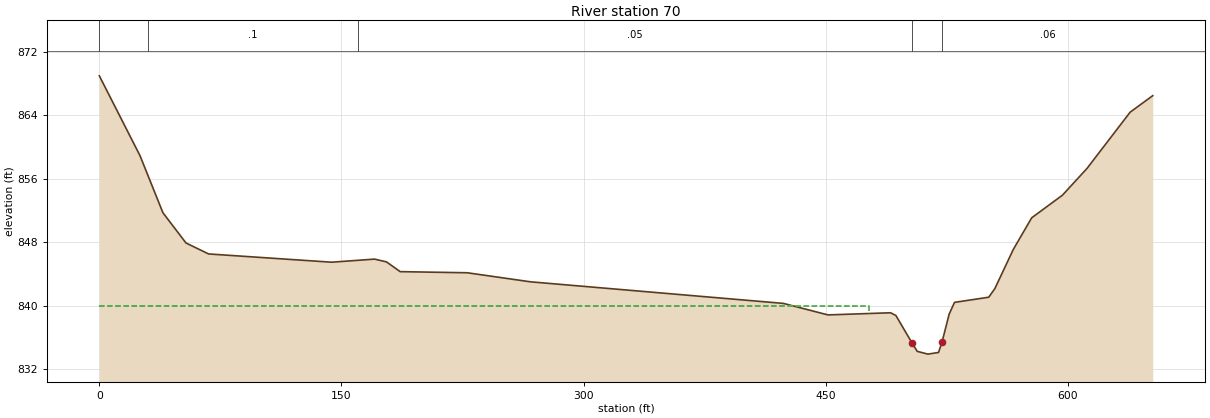
Type RM Length L Ch R = 1 ,70      ,,,
XS GIS Cut Line= 4
1632742.52950381534911.078612823 1632300.7095095534726.213338403
  1632239.325284534719.9165647371632142.92661337534776.825395184
#Sta/Elev= 30
       0  868.95    25.2  858.89    39.4   851.7    53.7  847.89    67.7  846.51
   143.9  845.47   170.5  845.86   177.9  845.51   186.4  844.28   227.9  844.14
   267.1     843   423.8  840.28   451.4  838.83   490.2   839.1   493.5  838.75
   503.4  835.32   506.7  834.24   513.3  833.89   519.9   834.1  522.05835.4047
   526.5  838.94   529.8  840.41     551  841.06   554.8  842.15   566.2  847.07
   577.6  851.06   596.7  853.92   611.9  857.29   638.6  864.37   652.6  866.45
#Mann= 5 ,-1,0
       0     .06       0      30      .1       0     160     .05       0
   503.4    .045       0  522.05     .06       0
#XS Ineff= 2 , 0
        476.6201  839.94
Permanent Ineff=
       T       F
Bank Sta=503.4,522.05
XS Rating Curve= 0 ,0
Exp/Cntr(USF)=0,0
Exp/Cntr=0.3,0.1
LCMann Table=0

Chan Stop Cuts=-1
Use User Specified Reach Order=0
Composite Channel Slope=5